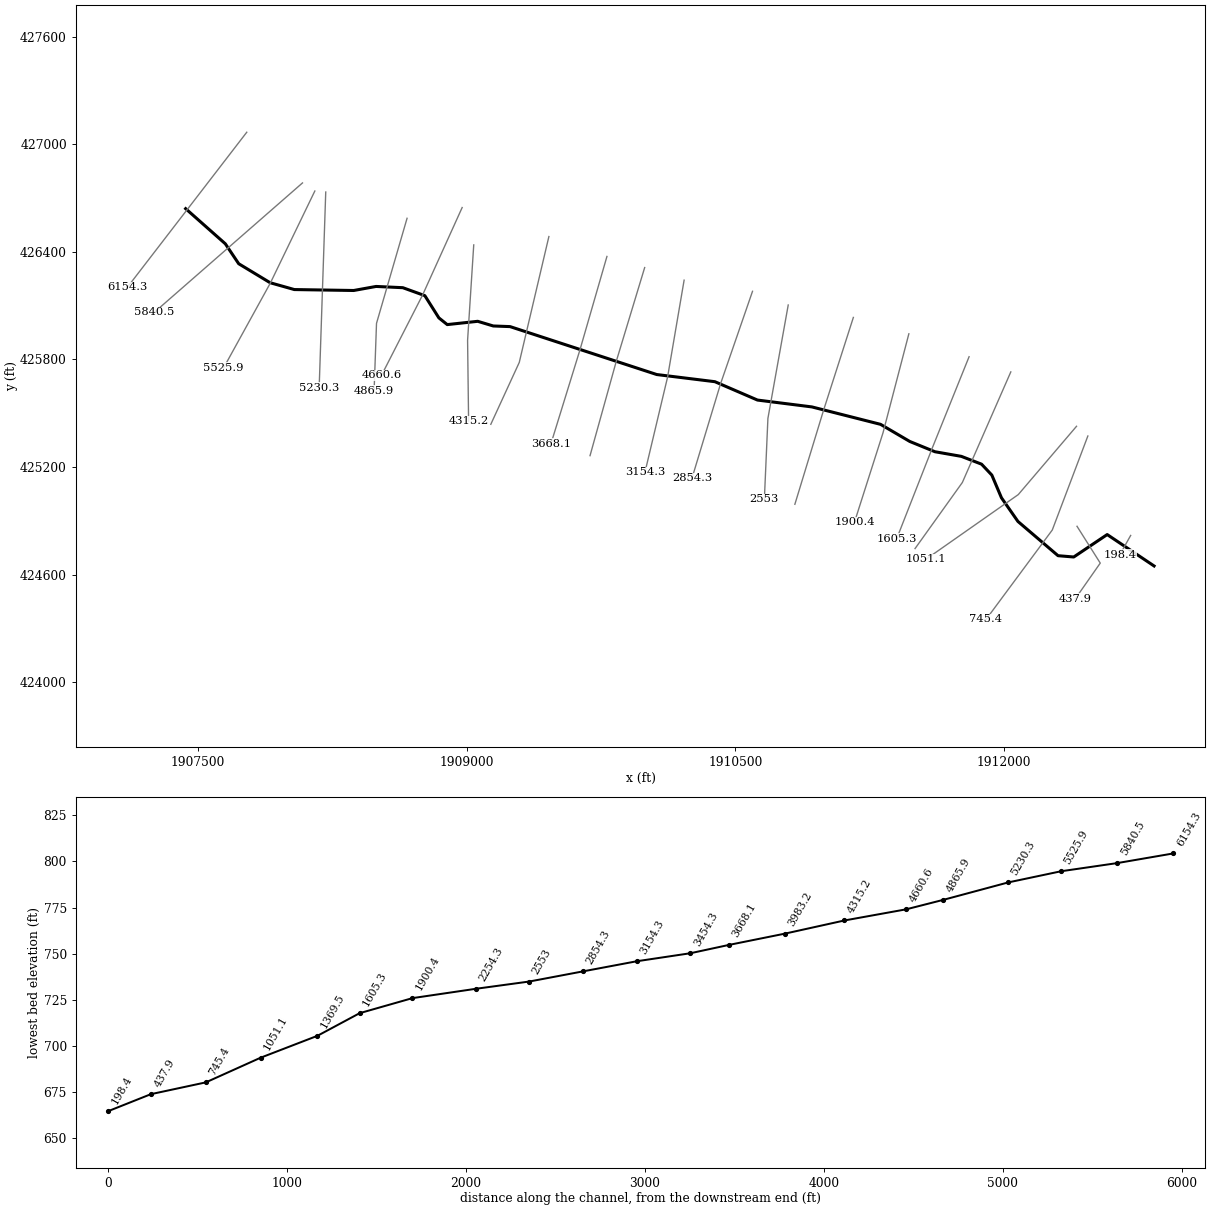
--- ScrabbleCk.prj (project) ---

Proj Title=ScrabbleCk
Current Plan=p01
Default Exp/Contr=0,0
English Units
Geom File=g01
Flow File=f01
Plan File=p01
BEGIN DESCRIPTION:
END DESCRIPTION:
DSS Export Rating Curves= 0
DSS Export Rating Curve Sorted= 0
DSS Export Volume Flow Curves= 0
DXF OffsetX= 0
DXF OffsetY= 0
DXF ScaleX= 0
DXF ScaleY= 0

--- ScrabbleCk.p01 (plan) ---

Plan Title=Floodplain
Program Version=4.00
Geom File=g01
Flow File=f01
K Sum by GR=0
Std Step Tol=0.01
Critical Tol=0.01
Num of Std Step Trials=20
Max Error Tol=0.3
Flow Tol Ratio=0.001
Split Flow NTrial=30
Split Flow Tol=0.02
Split Flow Ratio=0.02
Log Output Level=0
Friction Slope Method=1
Unsteady Friction Slope Method=2
Unsteady Bridges Friction Slope Method=1
Global Log Level=0
CheckData=False
Run HTab=0
Run UNet=0
Run PostProcess=0
UNET Theta=0
UNET Theta Warmup=0
UNET ZTol=0
UNET ZSATol=0
UNET MxIter=0
UNET MaxInSteps=0
UNET DtIC=0
UNET DtMin=0
UNET MaxCRTS=0
UNET WFStab=0
UNET SFStab=0
UNET WFX=0
UNET SFX=0
UNET DSS MLevel=0
UNET DZMax Abort=0
UNET Convert EG Bridges=0
UNET Use Existing IB Tables=0
UNET Froude Limit=0
UNET Froude Power=0
Write IC File=0
Echo Input=False
Echo Output=False
Write Detailed=0

--- ScrabbleCk.f01 (steady flow) ---

Flow Title=NFF Regression Equation
Program Version=4.00
Number of Profiles=1
Profile Names=P100yr
River Rch & RM=ScrabbleCk,Main      ,6154.3
829.2679
River Rch & RM=ScrabbleCk,Main      ,5525.9
844.5623
River Rch & RM=ScrabbleCk,Main      ,198.4
931.8369
Boundary for River Rch & Prof#=ScrabbleCk,Main      ,1
Up Type=0
Dn Type=3
Dn Slope=0.034423

--- ScrabbleCk.g01 (geometry) ---

Geom Title=USGS 3m DEM
Program Version=4.10

River Reach=ScrabbleCk      ,Main
Reach XY= 30
     1907430.082      426640.519     1907651.745      426444.498
     1907726.397      426333.387     1907901.744      426227.484
     1908037.161       426189.29     1908368.759      426184.081
     1908493.758      426206.651     1908643.064      426199.706
     1908766.039      426155.311     1908844.453      426031.304
       1908891.2       425993.88     1909061.467      426012.206
     1909148.272      425986.164     1909242.022      425982.692
     1910061.467      425715.331     1910386.119      425675.401
     1910623.967       425572.97     1910927.786      425534.776
     1911311.467      425437.553     1911474.661      425342.067
     1911615.286      425284.776     1911762.921      425258.903
     1911875.703      425215.331     1911932.995      425154.567
     1911986.814      425027.831     1912078.828      424895.887
     1912302.786      424704.915     1912390.586       424697.68
     1912577.294      424822.835     1912839.244      424647.623

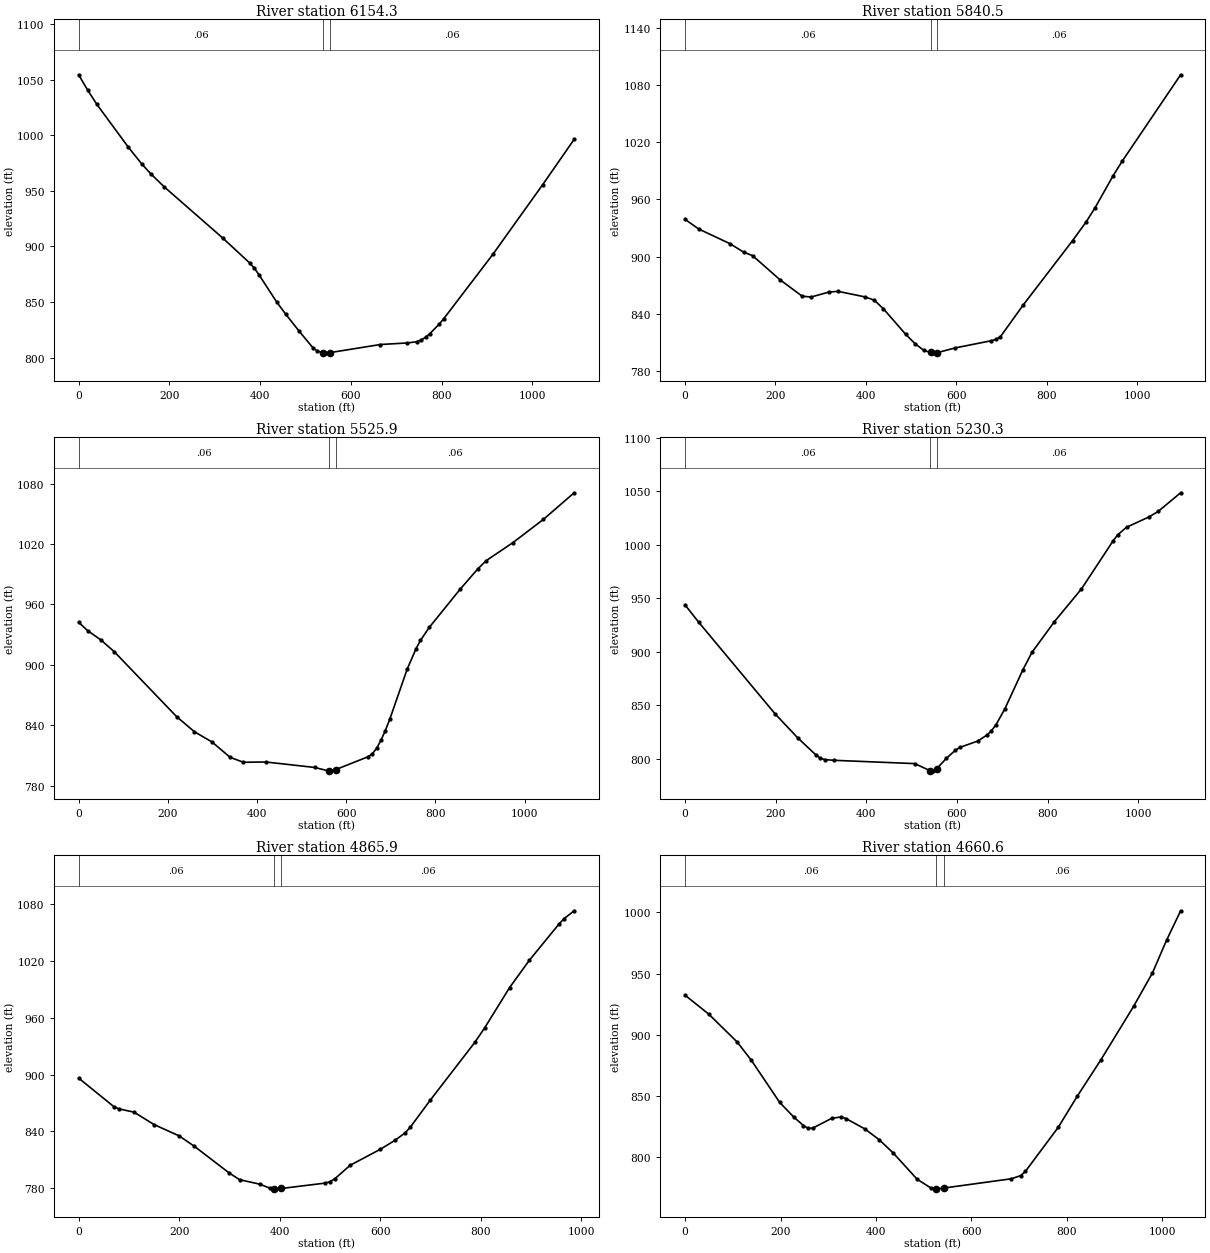
Type RM Length L Ch R = 1 ,6154.3  ,318.2,313.7,309.3
XS GIS Cut Line= 3
     1907771.406      427066.798     1907438.001      426634.413
     1907104.596      426202.027
#Sta/Elev= 30
       0 1054.45    19.8 1040.75    39.7  1028.1   109.2  989.51     139   974.3
   158.8  965.45   188.6  953.63   317.7  907.56   377.2  885.06   387.2  880.48
   397.1  874.75   436.8  849.86   456.6  838.98   486.4  823.57   516.2  808.94
   526.1  805.89   538.5  804.49     546  804.34   553.5  804.51   665.1  811.84
   724.7  813.24   744.6  814.29   754.5   815.8   764.4  818.29   774.3  821.72
   794.2  830.02   804.1  834.77   913.3   893.2  1022.5  955.54    1092  996.39
#Mann= 3 , 0 , 0
       0     .06       0   538.5    .045       0   553.5     .06       0
Bank Sta=538.5,553.5
XS Rating Curve= 0 ,0
Exp/Cntr=0.3,0.1

Type RM Length L Ch R = 1 ,5840.5  ,305.5,314.6,322.5
XS GIS Cut Line= 2
     1908082.685      426784.022     1907256.286      426063.304
#Sta/Elev= 30
       0  938.93    29.9   928.9    99.7  913.39   129.6   904.6   149.5  900.89
   209.3  875.94   259.2   858.4   279.1  857.62     319  862.86   338.9  863.49
   398.7  857.65   418.7  854.22   438.6  845.38   488.4  818.38   508.4  808.86
   528.3  801.65   543.4  799.46   548.3   799.1   558.4  799.34   598.1   804.3
   677.8  811.82   687.8  813.12   697.8  816.02   747.6  848.87   857.3  916.63
   887.2  936.15   907.1  951.07     947  984.61   966.9  999.72  1096.5 1090.46
#Mann= 3 , 0 , 0
       0     .06       0   543.4    .045       0   558.4     .06       0
Bank Sta=543.4,558.4
XS Rating Curve= 0 ,0
Exp/Cntr=0.3,0.1

Type RM Length L Ch R = 1 ,5525.9  ,286.1,295.6,306.2
XS GIS Cut Line= 3
     1908151.603      426738.903     1907903.491      426226.187
     1907641.741      425751.768
#Sta/Elev= 30
       0  942.31      20  934.05      50   924.7    79.9  913.06   219.8   848.5
   259.8  833.51   299.8  823.14   339.8  808.05   369.7  803.17   419.7  803.46
   529.6  798.02   559.6  794.66   561.3   794.7   576.3  795.86   648.4  808.52
   658.3  811.37   668.1  816.92     678  824.91   687.8  834.64   697.7   845.8
   737.1     896   756.8  916.06   766.6   924.2   786.3  937.18   855.3  974.95
   894.7  995.11   914.4 1003.66   973.5 1021.27  1042.5  1044.6  1111.4    1071
#Mann= 3 , 0 , 0
       0     .06       0   561.3    .045       0   576.3     .06       0
Bank Sta=561.3,576.3
XS Rating Curve= 0 ,0
Exp/Cntr=0.3,0.1

Type RM Length L Ch R = 1 ,5230.3  ,370.2,364.4,358.7
XS GIS Cut Line= 2
     1908212.571       426733.38     1908175.781      425640.453
#Sta/Elev= 30
       0  943.67    29.8  927.63   198.8  841.77   248.5  819.44   288.3   803.6
   298.2  800.48   308.2   799.1   328.1  798.46     507  795.35   539.9  788.86
   546.8   788.6   554.9   790.4   576.6  800.29   596.5  807.85   606.4  810.51
   646.2   816.5   666.1  822.04     676  826.05     686  831.63   705.8  846.66
   745.6  883.17   765.5  899.35   815.2  928.16   874.8  958.68   944.4 1003.48
   954.4 1009.13   974.2  1016.3    1024    1026  1043.8 1031.04  1093.6 1048.53
#Mann= 3 , 0 , 0
       0     .06       0   539.9    .045       0   554.9     .06       0
Bank Sta=539.9,554.9
XS Rating Curve= 0 ,0
Exp/Cntr=0.3,0.1

Type RM Length L Ch R = 1 ,4865.9  ,208.3,205.2,201.1
XS GIS Cut Line= 3
     1908666.783      426586.842     1908496.141      426000.863
     1908482.698      425625.167
#Sta/Elev= 30
       0  896.29      70  866.14      80  863.74   110.1  860.28   150.1  847.13
   200.1  835.14   230.1  824.22   300.2   795.7   320.2  788.82   360.2  784.08
   380.2  779.94   388.5  779.25   390.2  779.11   403.5  779.49   490.3  785.16
   500.3  786.69   510.3  789.93   540.3  804.01   600.3   820.9   630.1  830.59
   649.9  838.38   659.8   844.1   699.4  872.62   788.4     934   808.2  949.48
   857.6  991.96   897.2 1021.03   956.6 1059.66   966.5 1065.14   986.3 1073.35
#Mann= 3 , 0 , 0
       0     .06       0   388.5    .045       0   403.5     .06       0
Bank Sta=388.5,403.5
XS Rating Curve= 0 ,0
Exp/Cntr=0.3,0.1

Type RM Length L Ch R = 1 ,4660.6  ,337.2,345.3,354.4
XS GIS Cut Line= 3
     1908974.567      426646.811     1908753.444      426158.783
     1908524.044      425711.093
#Sta/Elev= 30
       0  932.26    49.6  916.81   109.1  894.07   138.9   879.1   198.4   844.6
   228.2  832.56     248  825.79     258  823.42   267.9  823.72   307.6   831.7
   327.4  832.79   337.4  831.44     377  822.96   406.8   814.2   436.6  803.23
   486.2  781.96   515.9  774.55   525.9  774.03   526.9  774.06   541.9  774.65
   683.7  782.25   703.5  784.84   713.3  788.26   782.4   824.4   821.8  849.57
   871.2  879.21   940.2  923.18   979.6   950.4  1009.2  977.14  1038.8 1001.29
#Mann= 3 , 0 , 0
       0     .06       0   526.9    .045       0   541.9     .06       0
Bank Sta=526.9,541.9
XS Rating Curve= 0 ,0
Exp/Cntr=0.3,0.1

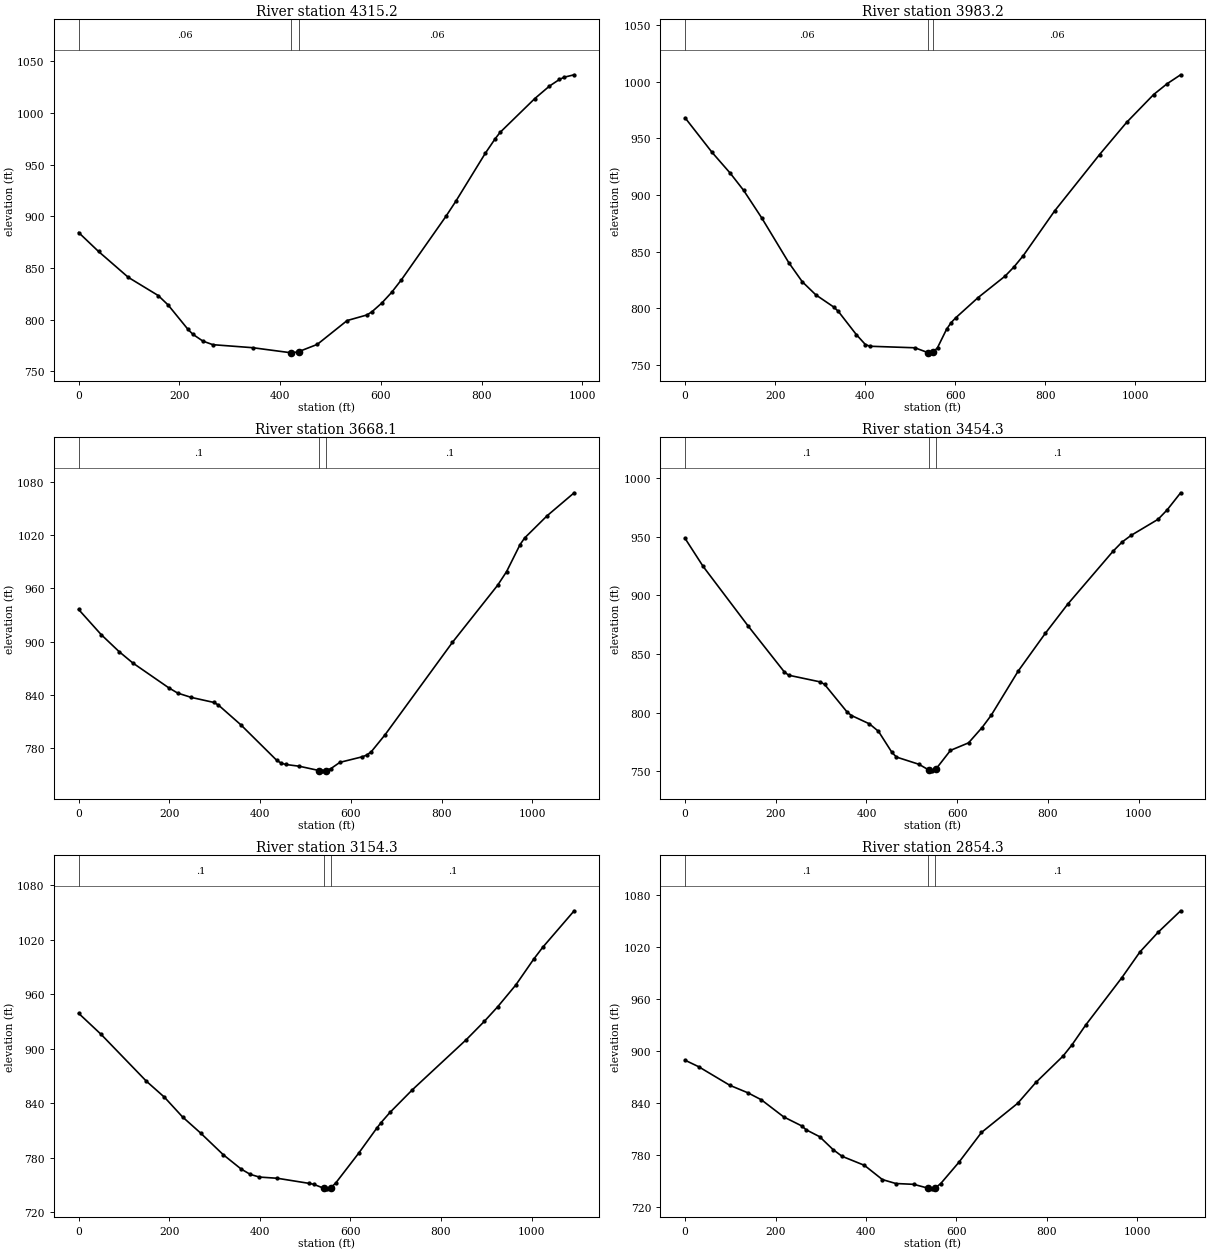
Type RM Length L Ch R = 1 ,4315.2  ,335.4,331.8,328.2
XS GIS Cut Line= 3
     1909039.191      426438.379     1909004.848      425906.419
     1909010.459      425455.593
#Sta/Elev= 30
       0  884.27    39.5  865.97    98.7  840.92     158  823.37   177.7  814.24
   217.2  790.62     227  785.83   246.8  779.31   266.5  775.86   345.5  772.95
   421.8  768.03   424.5  767.98   436.8  769.12   473.8  776.13   533.1  799.19
   572.3  804.57   582.1  807.58   601.7     816   621.3  826.31   640.9  838.59
   729.1  899.78   748.7  914.32   807.5  960.91   827.1  974.94   836.9   981.1
   905.5 1013.64   934.9 1025.83   954.5 1032.17   964.3 1034.41   983.9 1036.73
#Mann= 3 , 0 , 0
       0     .06       0   421.8    .045       0   436.8     .06       0
Bank Sta=421.8,436.8
XS Rating Curve= 0 ,0
Exp/Cntr=0.3,0.1

Type RM Length L Ch R = 1 ,3983.2  ,316.2,315.1,313.7
XS GIS Cut Line= 3
     1909458.957      426484.997     1909293.545      425782.999
     1909134.563      425437.801
#Sta/Elev= 30
       0  968.04    60.1  937.51   100.2  919.29   130.2  904.03   170.3   879.8
   230.4  840.38   260.4  823.55   290.5  811.99   330.6  801.17   340.6  797.37
   380.6  776.93   400.7  768.16   410.7  766.67   510.9  765.31   540.9  760.86
   550.9  761.34     561  765.42     581  781.57     591  787.38     601  791.58
   651.1  809.56   711.2  828.51   731.2  836.72   751.2  846.36   821.2  885.94
   921.2   935.7   981.3  964.06  1041.3  988.57  1071.3  998.11  1101.3 1005.99
#Mann= 3 , 0 , 0
       0     .06       0   540.9    .045       0   550.9     .06       0
Bank Sta=540.9,550.9
XS Rating Curve= 0 ,0
Exp/Cntr=0.3,0.1

Type RM Length L Ch R = 1 ,3668.1  ,214.1,213.8,214.2
XS GIS Cut Line= 3
     1909783.206      426373.944       1909631.4       425849.52
     1909469.932      425327.668
#Sta/Elev= 30
       0  936.37    49.6  908.13    89.3  888.88   119.1  876.26   198.5  848.23
   218.4  842.22   248.2  837.38   297.8  831.74   307.7  828.94   357.4  806.58
   436.8  766.44   446.7  763.33   456.6  761.86   486.4  759.87   529.7  755.06
     536   754.7   544.7  755.06   555.9   757.2   575.8  764.25   625.4  770.54
   635.3  772.54   645.3  776.41   675.1  795.12     824  899.44   923.4  963.57
   943.2  978.99     973 1009.49     983 1016.86  1032.6 1041.91  1092.2 1067.76
#Mann= 3 , 0 , 0
       0      .1       0   529.7    .045       0   544.7      .1       0
Bank Sta=529.7,544.7
XS Rating Curve= 0 ,0
Exp/Cntr=0.3,0.1

Type RM Length L Ch R = 1 ,3454.3  ,297.2,300,300.8
XS GIS Cut Line= 3
     1909993.959       426311.97     1909835.626      425790.015
     1909688.771      425262.808
#Sta/Elev= 30
       0  948.56    39.7  924.73   138.8  873.94   218.2  834.95   228.1  831.86
   297.5  826.17   307.4  824.08     357  800.52   366.9  797.44   406.6  790.29
   426.4  783.94   456.2  765.88   466.1  761.97   515.7   755.8   537.9  750.82
   545.4  750.22   552.9  751.64   585.2  767.68     625   774.1   654.9   787.2
   674.8  797.54   734.5  835.37   794.2  867.54     844  892.62   943.5  937.59
   963.4  945.44   983.3  951.14    1043  964.93  1062.9  972.92  1092.7  987.55
#Mann= 3 , 0 , 0
       0      .1       0   537.9    .045       0   552.9      .1       0
Bank Sta=537.9,552.9
XS Rating Curve= 0 ,0
Exp/Cntr=0.3,0.1

Type RM Length L Ch R = 1 ,3154.3  ,303.7,300,298.7
XS GIS Cut Line= 3
     1910214.272       426241.66     1910121.892      425700.944
     1909995.531       425170.23
#Sta/Elev= 30
       0  938.88    49.9  915.58   149.6  864.21   189.5   846.6   229.4  824.95
   269.3  807.23   319.2  783.44     359  767.57     379  761.78     399  758.82
   438.8  757.49   508.7  751.89   518.6  750.91   541.1  746.56   548.6  745.87
   556.1  747.32   558.5  747.79   568.4  752.78     618  784.86   657.7  812.22
   667.6  818.61   687.4   829.9     737  854.88     856  909.95   895.7  930.01
   925.5  946.22   965.2  970.02  1004.8  998.47  1024.7 1011.48  1094.1 1051.62
#Mann= 3 , 0 , 0
       0      .1       0   541.1    .045       0   556.1      .1       0
Bank Sta=541.1,556.1
XS Rating Curve= 0 ,0
Exp/Cntr=0.3,0.1

Type RM Length L Ch R = 1 ,2854.3  ,297.7,301.2,303.8
XS GIS Cut Line= 3
      1910596.33      426179.595     1910417.984      425664.371
     1910258.342      425137.602
#Sta/Elev= 30
       0  888.77    29.7  881.38    99.1  859.79   138.8   851.2   168.5  843.16
   218.1  823.36   257.7  813.04   267.6  808.54   297.4  800.57   327.1  785.72
     347  777.94   396.5   767.5   436.2  751.08   465.9  746.53   505.6  745.59
   537.7  741.07   545.2  740.39   552.7  741.26   565.2   746.5   605.3  771.01
   655.3  805.44   735.4  839.13   775.4  863.09   835.4  893.46   855.5  906.62
   885.5  929.25   965.6  984.01  1005.6 1013.73  1045.6 1036.33  1095.6 1061.22
#Mann= 3 , 0 , 0
       0      .1       0   537.7    .045       0   552.7      .1       0
Bank Sta=537.7,552.7
XS Rating Curve= 0 ,0
Exp/Cntr=0.3,0.1

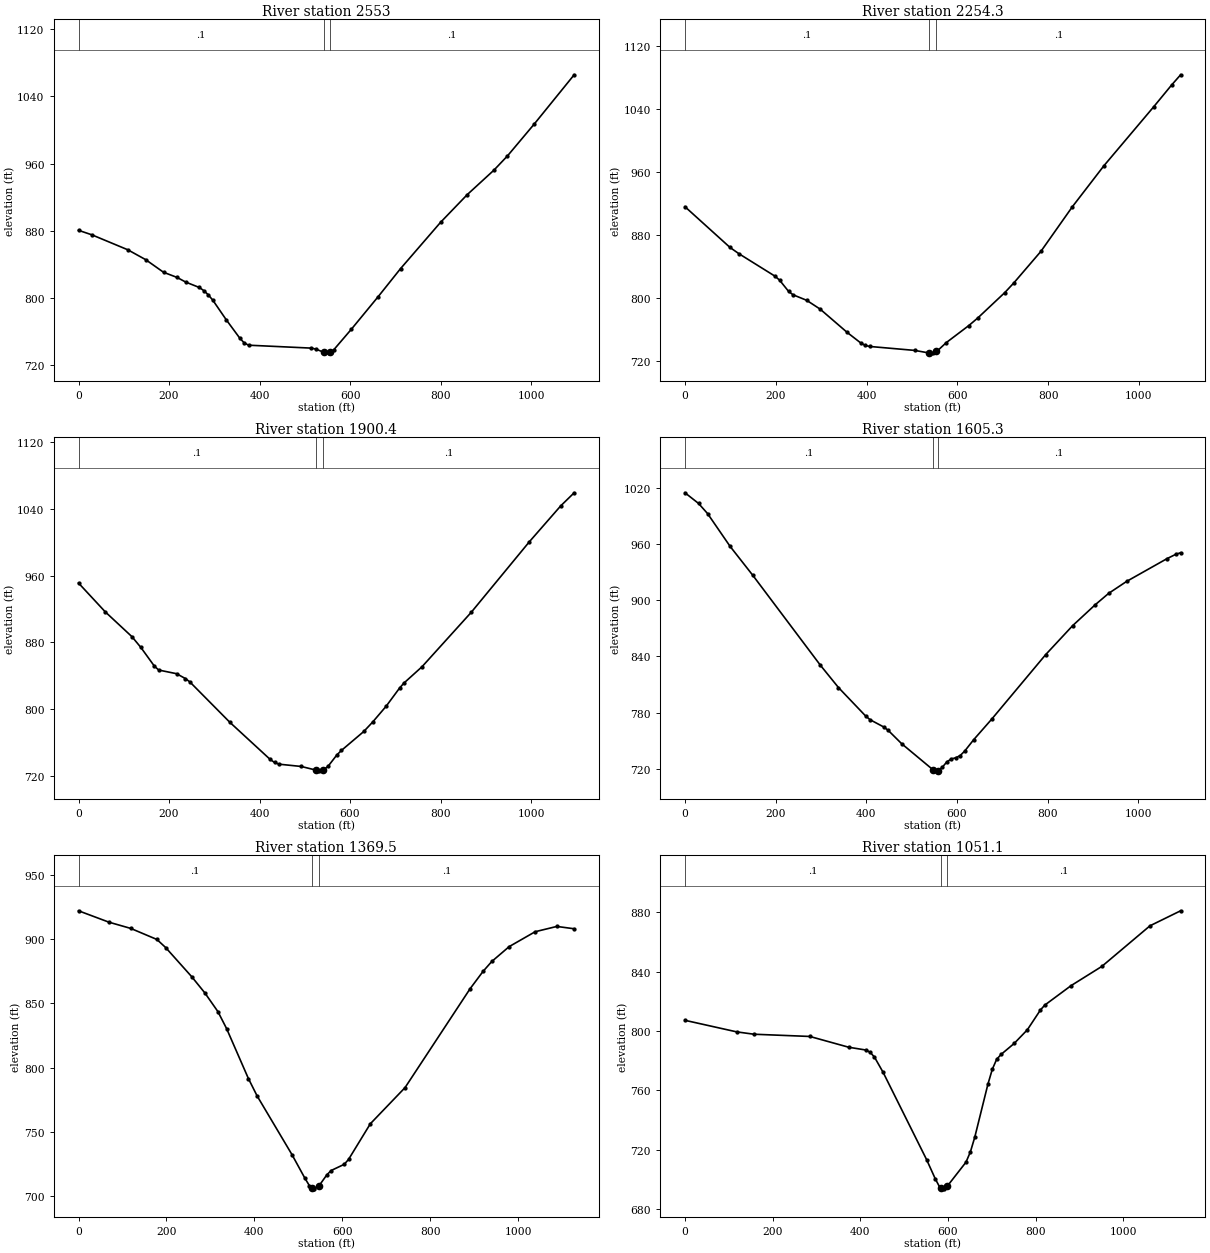
Type RM Length L Ch R = 1 ,2553    ,301.7,298.7,296
XS GIS Cut Line= 3
      1910795.75       426103.09     1910682.294      425470.691
      1910662.46      425018.753
#Sta/Elev= 30
       0  880.58    29.6   875.2   108.7  857.47   148.3  845.71   187.8  830.69
   217.5  824.59   237.2  818.93   266.9  812.59   276.8  808.86   286.6  803.88
   296.5  797.62   326.2   774.3   355.8  752.66   365.7  746.81   375.6  743.96
     514  740.49   523.9  739.39   541.2  735.66   553.5  734.87   556.2  735.78
   563.4  738.21     603  763.11   662.2  801.85   711.3  834.98   799.8  890.09
   858.8  923.06   917.8   952.2   947.4  968.95  1006.4 1006.76  1094.9 1065.54
#Mann= 3 , 0 , 0
       0      .1       0   541.2    .045       0   556.2      .1       0
Bank Sta=541.2,556.2
XS Rating Curve= 0 ,0
Exp/Cntr=0.3,0.1

Type RM Length L Ch R = 1 ,2254.3  ,352.5,353.8,354.7
XS GIS Cut Line= 3
     1911159.534      426033.785     1910992.457      425513.989
     1910832.907      424991.748
#Sta/Elev= 30
       0  916.22    99.3  864.54   119.1  856.54   198.5  828.09   208.5  823.06
   228.3  808.85   238.2  804.52     268  797.58   297.8  786.38   357.4  756.83
   387.2  743.49   397.1  740.34     407  739.02   506.3  734.01   536.1  730.93
   538.5  730.93     546  730.94   553.5  732.74   555.9  733.32   575.8  743.93
   625.4  765.52   645.3  775.22   704.8  807.42   724.7  819.68   784.3  859.66
   853.8   916.4   923.3  968.36  1032.5 1042.78  1072.2 1070.55  1092.1 1083.55
#Mann= 3 , 0 , 0
       0      .1       0   538.5    .045       0   553.5      .1       0
Bank Sta=538.5,553.5
XS Rating Curve= 0 ,0
Exp/Cntr=0.3,0.1

Type RM Length L Ch R = 1 ,1900.4  ,297.9,295.1,292.4
XS GIS Cut Line= 3
     1911469.591      425942.649     1911325.153      425390.199
     1911165.471       424890.79
#Sta/Elev= 30
       0  951.31    59.1  916.72   118.1   886.9   137.8  873.99   167.4  851.74
   177.2  846.87   216.6  842.49   236.3  836.61   246.1  832.58   334.7  783.99
   423.3  739.69   433.2   735.9     443  733.88   492.3  731.12     525  726.72
   531.6  725.88     540  726.58   551.3  731.22     571  745.02   580.9  750.33
   630.4  773.12   650.2  784.55   679.8  803.42   709.5  825.26   719.4  831.39
     759  850.79   867.8  916.12   996.4 1000.92  1065.7 1043.98  1095.3 1059.64
#Mann= 3 , 0 , 0
       0      .1       0     525    .045       0     540      .1       0
Bank Sta=525,540
XS Rating Curve= 0 ,0
Exp/Cntr=0.3,0.1

Type RM Length L Ch R = 1 ,1605.3  ,236.5,235.7,234.8
XS GIS Cut Line= 3
     1911805.952      425814.663     1911600.916      425306.917
     1911401.372      424798.987
#Sta/Elev= 30
       0 1015.03    29.9 1003.66    49.8  992.81    99.6  957.67   149.3  926.97
   298.7  830.62   338.5  806.82   398.2   776.5   408.2  772.41   438.1  764.69
     448  761.13   477.9  746.76   547.6  718.65   557.5  717.72   567.4  721.42
   577.4  727.19   587.3  730.45   597.2  731.65   607.1  734.06     617  738.86
   636.9  751.06   676.6     773   795.6  841.97   855.2     873   904.8  895.26
   934.6   907.5   974.2  920.28  1063.5  944.67  1083.4  949.42  1093.3  950.89
#Mann= 3 , 0 , 0
       0      .1       0   547.6    .045       0   557.5      .1       0
Bank Sta=547.6,557.5
XS Rating Curve= 0 ,0
Exp/Cntr=0.3,0.1

Type RM Length L Ch R = 1 ,1369.5  ,330.8,318.4,306
XS GIS Cut Line= 3
     1912039.009       425730.03     1911768.394      425113.308
     1911504.115      424744.591
#Sta/Elev= 30
       0  922.21    69.3  913.31   118.8  908.46   178.3  899.84   198.1  893.57
   257.5  870.79   287.2  858.23   316.9  843.66   336.7   830.4   386.3  791.45
   406.1   777.9   485.3   732.2     515   713.6   524.9  708.01   531.1  706.41
   534.8  705.46   546.1  707.45   564.5  716.26   574.4  719.73   604.2  724.56
   614.1  728.41   663.6  756.18   742.5  784.36   890.4  861.43     920  875.01
   939.8  882.69   979.2  894.25  1038.4  905.88  1087.7  910.01  1127.1  908.18
#Mann= 3 , 0 , 0
       0      .1       0   531.1    .045       0   546.1      .1       0
Bank Sta=531.1,546.1
XS Rating Curve= 0 ,0
Exp/Cntr=0.3,0.1

Type RM Length L Ch R = 1 ,1051.1  ,298.4,305.6,312.9
XS GIS Cut Line= 3
     1912406.103      425426.755     1912080.702      425045.695
     1911564.878      424684.782
#Sta/Elev= 30
       0   807.2   117.9  799.41   157.2  797.82   284.9  796.31   373.4  789.05
   412.7  787.16   422.5  785.62   432.3  782.36     452  772.08   551.1  713.28
     571  700.25     581  694.73   583.7  694.41     591  693.55   598.7   695.5
     641  711.54     651  718.44     661  728.34     691  764.12     701  774.16
   710.9  780.88   720.9  784.16   750.9   791.6   780.9  800.79   810.9  814.21
   820.9   817.5   880.8  830.61   950.8  843.54  1060.7  870.94  1130.6  881.07
#Mann= 3 , 0 , 0
       0      .1       0   583.7    .045       0   598.7      .1       0
Bank Sta=583.7,598.7
XS Rating Curve= 0 ,0
Exp/Cntr=0.3,0.1

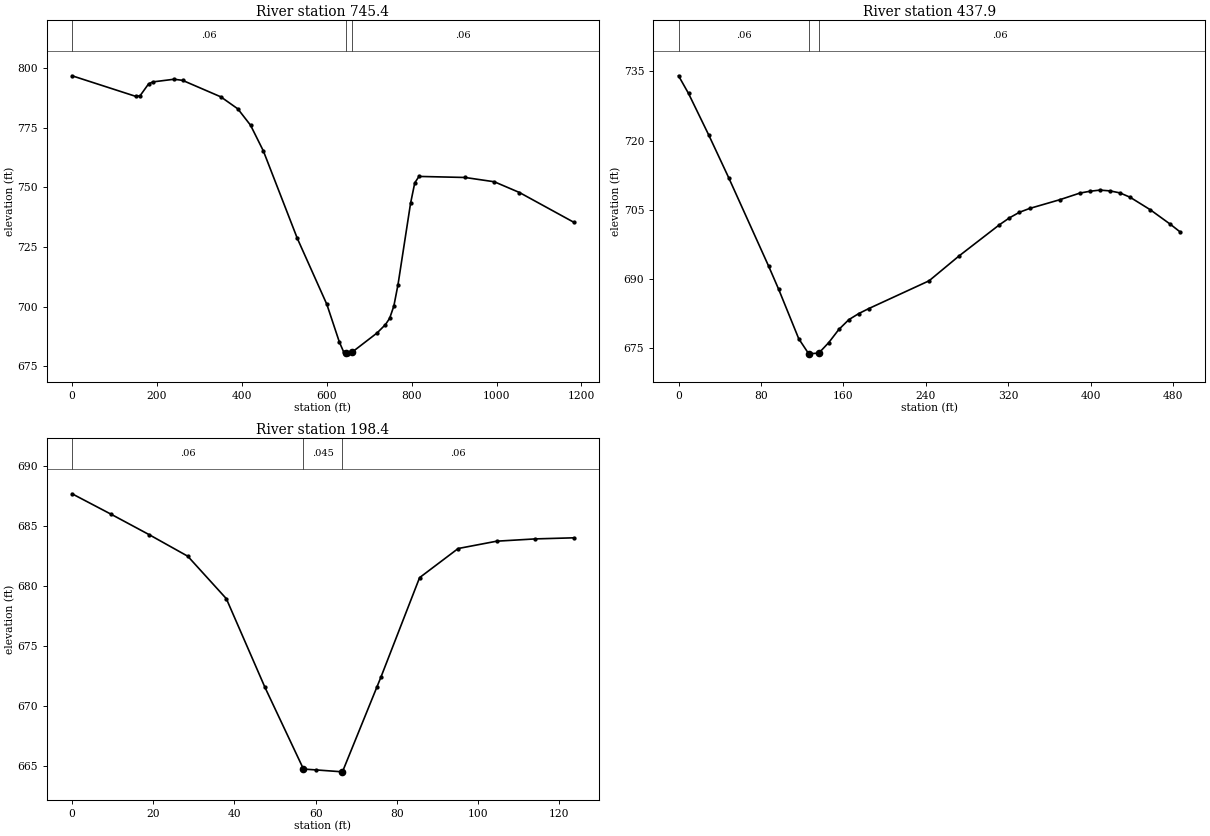
Type RM Length L Ch R = 1 ,745.4   ,279.9,307.3,334.7
XS GIS Cut Line= 3
     1912469.363      425372.548     1912270.662      424848.222
     1911900.411      424349.149
#Sta/Elev= 30
       0  796.76   150.2  788.12   160.2  788.39   180.2  793.35   190.2  794.19
   240.3  795.31   260.3  794.84   350.4  787.93   390.5  782.89   420.5  776.02
   450.6  765.27   530.7  728.56   600.2  700.94   629.8  685.08   639.6  681.09
   644.9  680.61   649.5   680.2   659.9  680.93   718.5  688.95   738.3  692.47
   748.1  695.09     758  700.21   767.8  709.18   797.4  743.29   807.3  751.86
   817.2  754.57   925.7  754.13   994.7  752.33  1053.9  747.83  1182.1  735.34
#Mann= 3 , 0 , 0
       0     .06       0   644.9    .045       0   659.9     .06       0
Bank Sta=644.9,659.9
XS Rating Curve= 0 ,0
Exp/Cntr=0.3,0.1

Type RM Length L Ch R = 1 ,437.9   ,264.2,239.5,214.8
XS GIS Cut Line= 3
      1912408.75      424868.971      1912538.61      424663.628
     1912398.733      424464.009
#Sta/Elev= 30
       0  734.07     9.7  730.23    29.2  721.27    48.6     712    87.5  692.75
    97.2  687.75   116.6  677.07   126.3   673.8   136.1  673.97   145.7  676.24
   155.5  679.09   165.2  681.21   174.9  682.54   184.6  683.62     243  689.63
   272.2  695.04   311.2  701.77     321  703.28   330.7  704.49   340.5  705.31
   369.7   707.2   389.2  708.64     399  709.04   408.7  709.29   418.5  709.12
   428.2  708.68     438  707.74   457.5  705.04     477  701.89   486.7  700.19
#Mann= 3 , 0 , 0
       0     .06       0   126.3    .045       0   136.1     .06       0
Bank Sta=126.3,136.1
XS Rating Curve= 0 ,0
Exp/Cntr=0.3,0.1

Type RM Length L Ch R = 1 ,198.4   ,198.5,198.3,198.1
XS GIS Cut Line= 2
     1912708.447      424817.904     1912648.078      424710.045
#Sta/Elev= 16
       0  687.66     9.5  685.98      19  684.26    28.5  682.47      38  678.94
    47.5  671.58      57  664.78    60.1  664.71    66.6  664.55    75.1  671.61
    76.1  672.44    85.6  680.69    95.1  683.11   104.6  683.72   114.1  683.91
   123.6     684
#Mann= 3 , 0 , 0
       0     .06       0      57    .045       0    66.6     .06       0
Bank Sta=57,66.6
XS Rating Curve= 0 ,0
Exp/Cntr=0.3,0.1

Chan Stop Cuts=-1
Use User Specified Reach Order=0
Composite Channel Slope=5